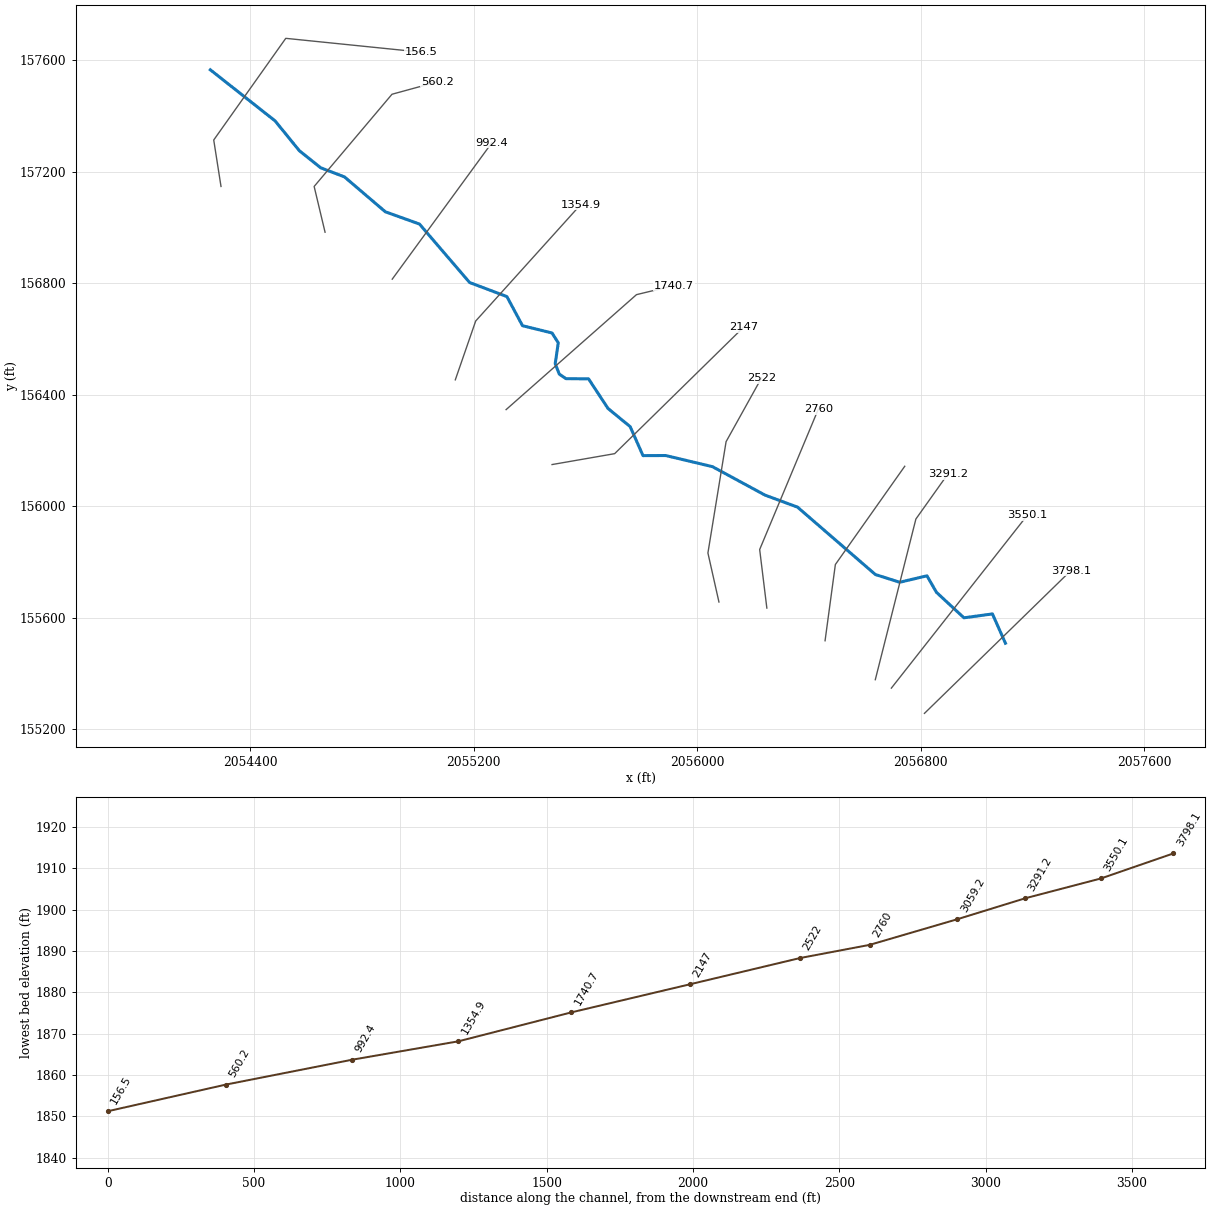
--- PNTRRN.prj (project) ---

Proj Title=PNTRRN
Current Plan=p01
Default Exp/Contr=0,0
English Units
Geom File=g01
Flow File=f01
Plan File=p01
BEGIN DESCRIPTION:
END DESCRIPTION:
DSS Export Rating Curves= 0
DSS Export Rating Curve Sorted= 0
DSS Export Volume Flow Curves= 0
DXF OffsetX= 0
DXF OffsetY= 0
DXF ScaleX= 0
DXF ScaleY= 0

--- PNTRRN.p01 (plan) ---

Plan Title=Floodplain
Program Version=4.00
Geom File=g01
Flow File=f01
K Sum by GR=0
Std Step Tol=0.01
Critical Tol=0.01
Num of Std Step Trials=20
Max Error Tol=0.3
Flow Tol Ratio=0.001
Split Flow NTrial=30
Split Flow Tol=0.02
Split Flow Ratio=0.02
Log Output Level=0
Friction Slope Method=1
Unsteady Friction Slope Method=2
Unsteady Bridges Friction Slope Method=1
Global Log Level=0
CheckData=False
Run HTab=0
Run UNet=0
Run PostProcess=0
UNET Theta=0
UNET Theta Warmup=0
UNET ZTol=0
UNET ZSATol=0
UNET MxIter=0
UNET MaxInSteps=0
UNET DtIC=0
UNET DtMin=0
UNET MaxCRTS=0
UNET WFStab=0
UNET SFStab=0
UNET WFX=0
UNET SFX=0
UNET DSS MLevel=0
UNET DZMax Abort=0
UNET Convert EG Bridges=0
UNET Use Existing IB Tables=0
UNET Froude Limit=0
UNET Froude Power=0
Write IC File=0
Echo Input=False
Echo Output=False
Write Detailed=0

--- PNTRRN.f01 (steady flow) ---

Flow Title=NFF Regression Equation
Program Version=4.00
Number of Profiles=1
Profile Names=P100yr
River Rch & RM=PNTRRN,Main      ,3798.1
591.5163
River Rch & RM=PNTRRN,Main      ,2147
603.3958
River Rch & RM=PNTRRN,Main      ,1740.7
801.0500
River Rch & RM=PNTRRN,Main      ,560.2
814.3898
River Rch & RM=PNTRRN,Main      ,156.5
815.9789
Boundary for River Rch & Prof#=PNTRRN,Main      ,1
Up Type=0
Dn Type=3
Dn Slope=0.014069

--- PNTRRN.g01 (geometry) ---

Geom Title=USGS 10m DEM
Program Version=4.10

River Reach=PNTRRN          ,Main
Reach XY= 30
     2057103.023      155508.832     2057056.451      155613.964
     2056954.455      155600.076     2056856.148      155691.471
     2056822.076      155750.683     2056724.551      155727.582
     2056637.397       155755.36     2056358.882      155996.951
     2056242.606      156040.082     2056054.411      156142.165
      2055887.05      156182.096       2055805.8      156181.749
     2055759.967      156285.568      2055680.41      156351.117
     2055611.009      156457.096     2055530.106       156457.79
     2055506.147       156474.11     2055491.564       156511.61
     2055502.675      156586.263     2055480.106      156621.679
      2055374.55      156647.721     2055318.647      156752.235
     2055185.314      156802.582       2055005.8      157012.304
     2054883.708      157056.239     2054737.398      157181.402
     2054651.938      157214.225     2054576.087      157275.054
     2054489.195      157382.178     2054257.299        157565.5

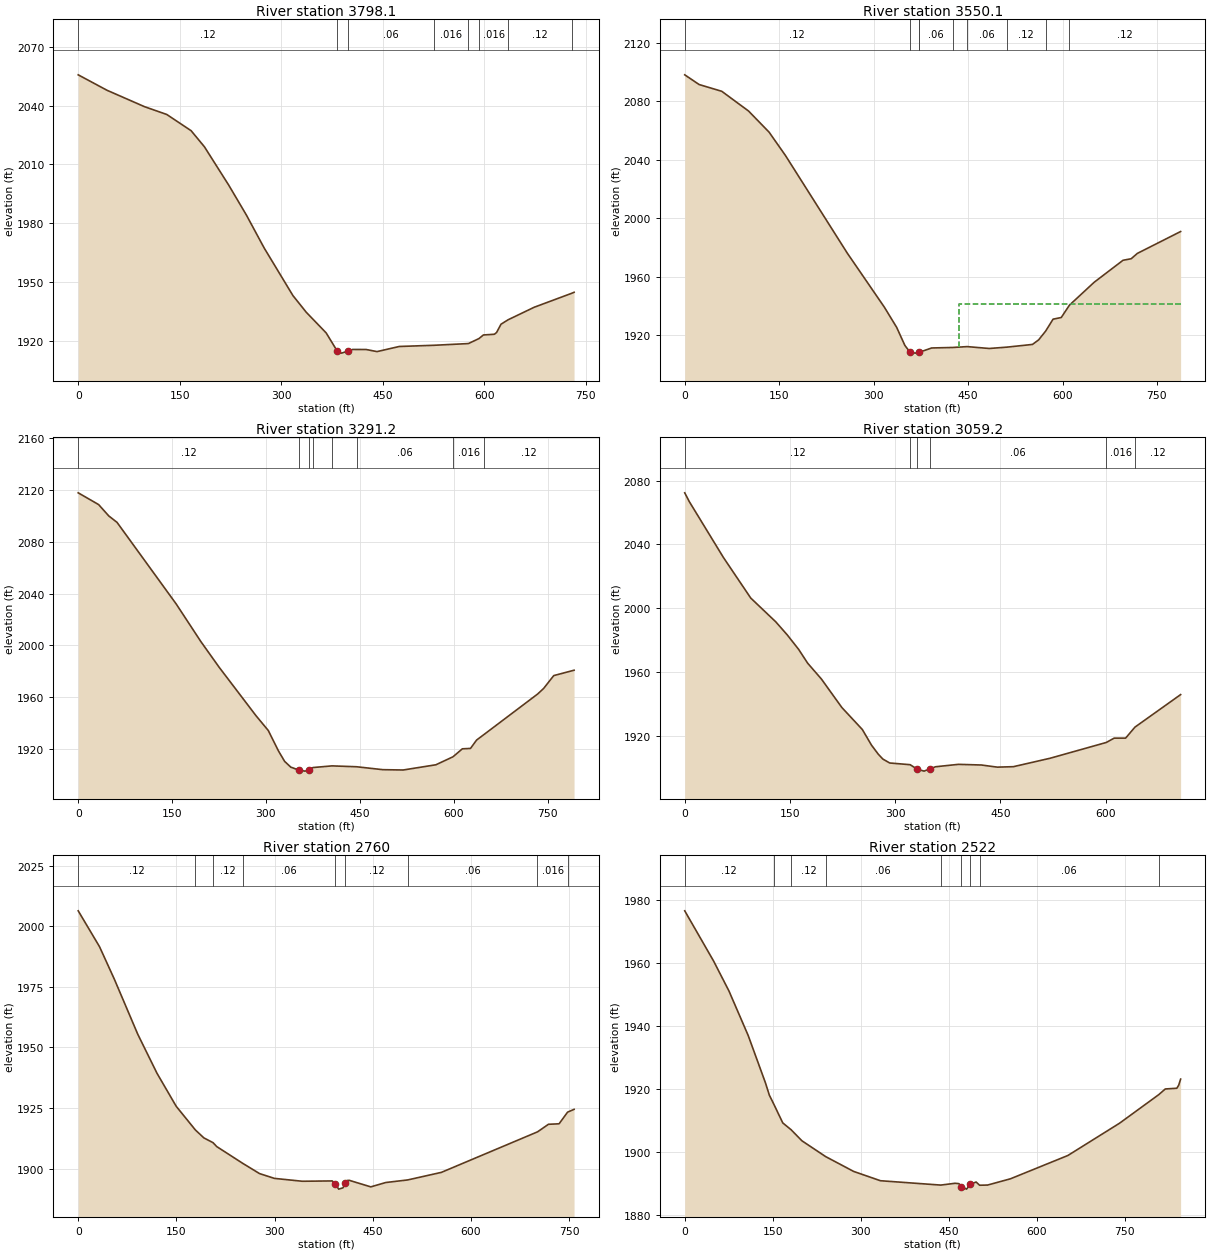
Type RM Length L Ch R = 1 ,3798.1  ,240.5,248.1,251.3
XS GIS Cut Line= 2
     2056813.093      155257.328     2057337.167      155769.513
#Sta/Elev= 30
       0 2055.67    42.5  2047.8    98.1  2039.4   130.9 2035.43   166.8 2027.17
   186.5 2018.96   222.5 1999.34   248.6 1984.07   274.8  1967.3   317.3 1943.02
     337  1934.5   366.4 1923.97   383.1 1914.51   389.3 1913.64   398.1 1914.65
   405.6 1915.51   425.3  1915.5   441.6 1914.42   474.4 1917.03   526.11917.648
  576.661918.518  592.281921.078   598.7  1922.9     615 1923.28   618.3 1924.18
   624.8  1928.4   635.31930.658   673.9 1937.06  730.051944.275   732.8  1944.7
#Mann= 8 ,-1 , 0
       0     .12       0   383.1    .045       0   398.1     .06       0
   526.1    .016       0  576.66     .06       0  592.28    .016       0
   635.3     .12       0  730.05     .06       0
Bank Sta=383.1,398.1
XS Rating Curve= 0 ,0
Exp/Cntr=0.3,0.1

Type RM Length L Ch R = 1 ,3550.1  ,247.9,258.9,266.9
XS GIS Cut Line= 2
     2056694.663      155347.898     2057180.917      155967.429
#Sta/Elev= 30
       0 2098.26    22.9  2091.6    58.8 2086.98   101.3 2073.48     134 2058.97
   160.1  2042.9   258.2 1976.07     317  1939.1   336.6 1925.23   349.7  1912.8
   357.3 1908.53     366 1907.57   372.3 1908.11  372.411908.128   392.2  1911.1
  425.711911.442  448.621912.034   483.6 1910.75  511.941911.681   552.3 1913.53
   562.1 1916.65  573.261922.692     585 1930.83     598 1931.97  611.051940.439
   650.3 1956.13   696.1 1971.18   709.1 1972.25   718.9 1975.91   787.6 1990.88
#Mann= 9 ,-1 , 0
       0     .12       0   357.3    .045       0   372.3     .12       0
  372.41     .06       0  425.71    .016       0  448.62     .06       0
  511.94     .12       0  573.26    .016       0  611.05     .12       0
#XS Ineff= 2 , 0
                          436.36         1941.02
Permanent Ineff=
       F       F
Bank Sta=357.3,372.3
XS Rating Curve= 0 ,0
Exp/Cntr=0.3,0.1

Type RM Length L Ch R = 1 ,3291.2  ,239.8,231.9,223.5
XS GIS Cut Line= 3
       2056637.2      155378.125     2056782.479      155954.409
     2056897.062      156115.867
#Sta/Elev= 30
       0 2117.85    32.6 2108.77      49 2099.92      62 2095.04   156.7 2031.86
   195.9 2002.95   225.3 1982.97   284.1 1945.59   303.7 1934.17     320 1918.34
   329.8 1910.31   339.6 1905.87     353 1903.48   362.5 1902.77     368 1903.42
   375.11905.535  405.561906.822  444.681906.147   486.6  1903.9   519.2 1903.64
   571.5 1907.68  598.781913.841   613.8 1920.01   626.8 1920.32   636.5 1926.77
  649.141931.354   733.9  1962.3   743.6 1966.64   759.8  1976.6   792.3 1980.76
#Mann= 8 ,-1 , 0
       0     .12       0     353    .045       0     368     .12       0
   375.1     .06       0  405.56    .016       0  444.68     .06       0
  598.78    .016       0  649.14     .12       0
Bank Sta=353,368
XS Rating Curve= 0 ,0
Exp/Cntr=0.3,0.1

Type RM Length L Ch R = 1 ,3059.2  ,293.1,299.2,303.1
XS GIS Cut Line= 3
     2056457.392      155517.777     2056494.285      155791.214
     2056742.559       156143.56
#Sta/Elev= 30
       0 2072.28     6.5 2066.77    55.2 2031.69    94.1 2006.28   129.8 1991.35
   146.1 1983.19   162.3 1974.14   175.3 1965.39   194.8 1955.51     224 1937.61
   253.2 1923.81   266.2 1914.05   275.9 1908.34   282.4 1905.29   292.2 1902.81
  321.361901.737   331.4 1898.94   341.2  1897.7   349.4 1899.11   357.6 1900.44
   390.2 1901.95   422.9 1901.54   445.7  1900.2   468.6 1900.49   520.8 1905.76
  601.011915.674   612.2 1918.39   628.6 1918.41  641.881925.298     707  1945.7
#Mann= 6 ,-1 , 0
       0     .12       0  321.36    .016       0   331.4    .045       0
   349.4     .06       0  601.01    .016       0  641.88     .12       0
Bank Sta=331.4,349.4
XS Rating Curve= 0 ,0
Exp/Cntr=0.3,0.1

Type RM Length L Ch R = 1 ,2760    ,232.3,238.1,243.1
XS GIS Cut Line= 3
     2056249.059      155634.964     2056223.371       155844.96
     2056433.521       156348.94
#Sta/Elev= 30
       0 2006.37    32.6 1991.55    55.3  1978.1    91.1 1955.37   120.4 1939.31
   149.7  1925.7  179.041915.911     192 1912.65  206.031910.674   211.6 1909.07
  251.521902.115     277 1897.92   299.8 1895.93   342.4 1894.75   388.1 1894.88
     393 1893.66   397.9  1891.5   404.5 1892.03     408 1893.85     411 1895.07
   414.3 1895.12     447 1892.43   469.9 1894.23  503.441895.294   554.9 1898.42
  701.691915.136   718.4 1918.26   734.7 1918.47  747.631923.269   757.6 1924.43
#Mann= 9 ,-1 , 0
       0     .12       0  179.04    .016       0  206.03     .12       0
  251.52     .06       0     393    .045       0     408     .12       0
  503.44     .06       0  701.69    .016       0  747.63     .06       0
Bank Sta=393,408
XS Rating Curve= 0 ,0
Exp/Cntr=0.3,0.1

Type RM Length L Ch R = 1 ,2522    ,387.8,374.9,358.7
XS GIS Cut Line= 4
     2056077.618      155656.666     2056038.158      155832.538
     2056103.169      156231.832     2056229.528      156459.617
#Sta/Elev= 30
       0 1976.44    49.2 1960.54    75.4 1951.05   108.2 1936.95   137.6 1921.96
   144.2 1918.08  151.411915.375   167.1 1909.28  181.331907.114   199.8 1903.61
  240.321898.599   287.9 1893.92   333.6 1890.97  436.45 1889.59   460.8 1890.16
   467.4 1890.04   471.7 1889.13   480.4 1888.31   486.7 1889.82   496.7 1890.56
   502.61889.544   516.3  1889.6   555.4 1891.59   653.2 1898.97   741.1 1909.17
  807.991918.223   819.2 1920.03   838.8 1920.25     842 1921.22   845.3 1923.14
#Mann= 9 ,-1 , 0
       0     .12       0  151.41    .016       0  181.33     .12       0
  240.32     .06       0  436.45     .12       0   471.7    .045       0
   486.7     .12       0   502.6     .06       0  807.99    .016       0
Bank Sta=471.7,486.7
XS Rating Curve= 0 ,0
Exp/Cntr=0.3,0.1

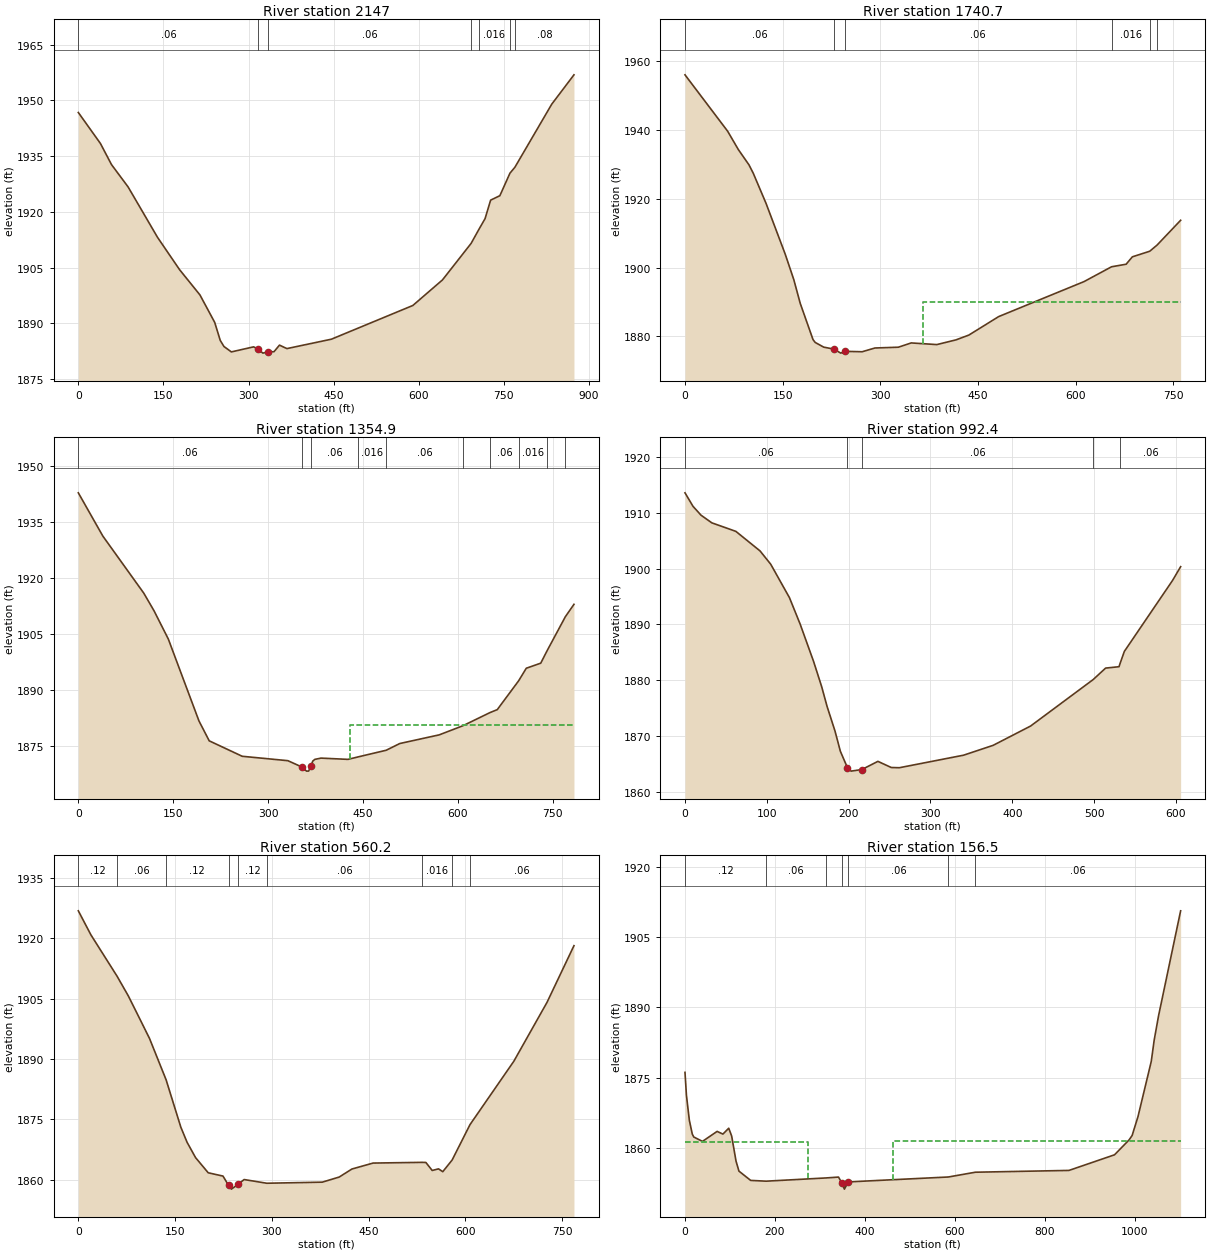
Type RM Length L Ch R = 1 ,2147    ,406.3,406.4,407.5
XS GIS Cut Line= 3
     2055480.396      156149.721     2055704.354      156188.784
     2056165.292      156641.909
#Sta/Elev= 30
       0 1946.77      39 1938.42    58.5 1932.74    87.7 1926.74   139.6 1913.16
   178.6 1904.43   214.4 1897.65   240.4 1890.26   250.2  1885.4   256.7 1883.77
   269.8 1882.31     309 1883.67   317.6    1883   325.3 1881.98   335.1 1882.34
   344.9 1882.36   354.6 1884.13   367.7  1883.2   446.1 1885.73   589.7 1894.81
   641.9 1901.69  692.371911.516  705.641915.166     717 1918.19   726.8 1923.17
   743.1 1924.37  760.861930.428  769.581932.023   834.5    1949   873.7 1956.91
#Mann= 7 ,-1 , 0
       0     .06       0   317.6    .045       0   335.1     .06       0
  692.37     .12       0  705.64    .016       0  760.86     .12       0
  769.58     .08       0
Bank Sta=317.6,335.1
XS Rating Curve= 0 ,0
Exp/Cntr=0.3,0.1

Type RM Length L Ch R = 1 ,1740.7  ,382.2,385.8,382.5
XS GIS Cut Line= 3
     2055315.899       156346.77     2055782.479      156759.096
     2055917.028      156791.648
#Sta/Elev= 30
       0 1955.96    65.5 1939.59    81.9 1934.27    98.3 1929.81   104.9 1927.36
   124.5 1918.62     154 1903.85   167.1 1896.49     177 1889.59   196.6 1879.09
   199.9 1878.27     213  1876.9   228.7 1876.33   239.2 1875.16   245.8 1875.68
     272 1875.56   291.7 1876.65   327.7 1876.88   347.4 1878.12   386.7 1877.64
   416.2 1879.01   435.9  1880.4   481.7 1885.77   612.8 1895.93  654.991900.229
   677.4 1900.97     687 1903.12   713.61904.738   724.81906.506   761.1 1913.73
#Mann= 6 ,-1 , 0
       0     .06       0   228.7    .045       0   245.8     .06       0
  654.99    .016       0   713.6     .08       0   724.8     .06       0
#XS Ineff= 2 , 0
                          364.95         1889.88
Permanent Ineff=
       F       F
Bank Sta=228.7,245.8
XS Rating Curve= 0 ,0
Exp/Cntr=0.3,0.1

Type RM Length L Ch R = 1 ,1354.9  ,357,362.5,363.9
XS GIS Cut Line= 3
     2055134.042      156453.541     2055206.958      156664.478
     2055581.958      157081.145
#Sta/Elev= 30
       0 1942.76    38.8 1931.16   103.5 1915.87   119.7 1911.15   142.3 1903.58
   190.8 1881.61     207 1876.28   259.2 1872.14   331.4 1870.96     353 1869.31
   360.9 1868.16   364.2 1868.18     368 1869.52   370.7 1870.84     374 1871.31
   383.8 1871.65   426.4 1871.31  442.261871.965  486.931873.758   508.4 1875.56
   570.7 1877.88  608.131880.319  650.951883.847   662.5 1884.64  696.431892.399
   708.4 1895.74   731.3  1897.1  740.59  1900.2  770.181909.548   783.8 1912.87
#Mann= 10 ,-1 , 0
       0     .06       0     353    .045       0     368     .06       0
  442.26    .016       0  486.93     .06       0  608.13     .12       0
  650.95     .06       0  696.43    .016       0  740.59     .12       0
  770.18     .06       0
#XS Ineff= 2 , 0
                          429.55         1880.52
Permanent Ineff=
       F       F
Bank Sta=353,368
XS Rating Curve= 0 ,0
Exp/Cntr=0.3,0.1

Type RM Length L Ch R = 1 ,992.4   ,433.3,432.2,428.5
XS GIS Cut Line= 2
     2054908.347      156814.652     2055265.118      157304.235
#Sta/Elev= 30
       0  1913.6     9.8 1911.18    19.6 1909.59    32.8 1908.22    62.2 1906.69
    91.7 1903.19   104.8  1900.8   127.7  1894.8   140.8 1890.05   157.2 1883.36
     167 1878.88   173.6 1875.34   183.4 1870.87   189.9 1867.27   198.5 1864.35
     203 1863.71   216.1 1863.99   235.8 1865.46   252.1 1864.36     262 1864.32
   340.6 1866.57   376.6 1868.33   422.4 1871.79  498.931880.127   514.1 1882.18
   530.5 1882.43  531.881883.049     537 1885.17     596 1897.91   605.8 1900.36
#Mann= 5 ,-1 , 0
       0     .06       0   198.5    .045       0   216.1     .06       0
  498.93    .016       0  531.88     .06       0
Bank Sta=198.5,216.1
XS Rating Curve= 0 ,0
Exp/Cntr=0.3,0.1

Type RM Length L Ch R = 1 ,560.2   ,400.7,403.8,404.8
XS GIS Cut Line= 4
     2054667.896      156983.054     2054628.833      157147.117
     2054907.479      157477.846     2055068.937      157522.117
#Sta/Elev= 30
       0 1926.77    19.5 1920.81   60.04 1910.55    77.8 1905.57   110.3 1895.12
  136.111884.822   158.9 1873.08   168.6 1869.32   181.8  1865.5   201.4 1861.74
   224.3 1860.92   232.9 1858.63   237.4 1857.68   247.9  1858.9   257.1 1860.06
  292.131859.141   378.3 1859.41   404.5 1860.68   424.2 1862.67     457 1864.15
  533.431864.327   538.9  1864.3   548.7 1862.31   558.5 1862.71   565.1 1862.01
   579.61864.906  607.291873.688   675.2 1889.41   726.7 1904.04   768.5 1918.12
#Mann= 9 ,-1 , 0
       0     .12       0   60.04     .06       0  136.11     .12       0
   232.9    .045       0   247.9     .12       0  292.13     .06       0
  533.43    .016       0   579.6     .12       0  607.29     .06       0
Bank Sta=232.9,247.9
XS Rating Curve= 0 ,0
Exp/Cntr=0.3,0.1

Type RM Length L Ch R = 1 ,156.5   ,160.8,156.5,152
XS GIS Cut Line= 4
       2054295.5      157147.117     2054269.458      157313.784
     2054527.271      157678.367     2055011.646      157628.888
#Sta/Elev= 30
       0 1876.13     3.2 1871.25     9.7  1865.9    16.2 1862.98    19.5 1862.35
    38.9 1861.41    71.4 1863.54    84.3 1862.97    97.3 1864.22   103.8 1862.55
   113.5  1857.2     120 1855.07     146 1853.09  180.551852.926  314.231853.619
   341.4  1853.8   348.2 1852.62   354.5 1851.23   363.2 1852.77  585.661853.818
   645.71854.837   853.8 1855.22   955.1 1858.55   987.7 1861.75   994.3 1862.68
  1007.4 1866.74  1036.8 1878.47  1043.3 1883.01  1053.1 1888.24  1102.1 1910.58
#Mann= 7 ,-1 , 0
       0     .12       0  180.55     .06       0  314.23     .12       0
   348.2    .045       0   363.2     .06       0  585.66    .016       0
   645.7     .06       0
#XS Ineff= 2 , 0
          274.43 1861.32  461.93         1861.41
Permanent Ineff=
       F       F
Bank Sta=348.2,363.2
XS Rating Curve= 0 ,0
Exp/Cntr=0.3,0.1

Chan Stop Cuts=-1
Use User Specified Reach Order=0
Composite Channel Slope=5